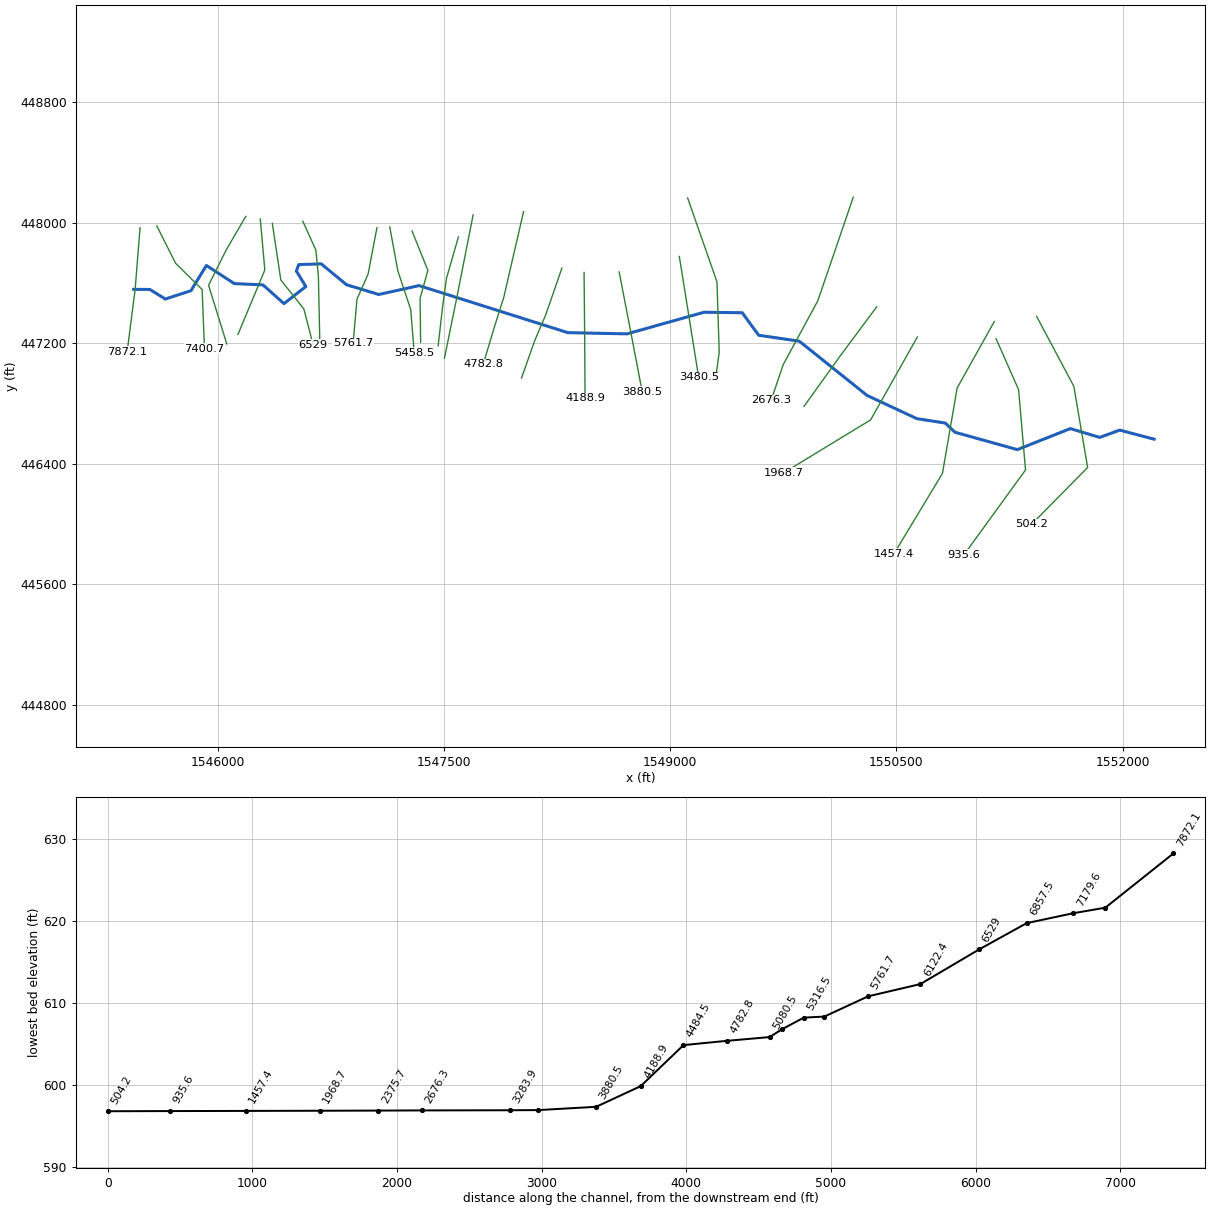
--- TOMSCR.prj (project) ---

Proj Title=TOMSCR
Current Plan=p01
Default Exp/Contr=0,0
English Units
Geom File=g01
Flow File=f01
Plan File=p01
BEGIN DESCRIPTION:
END DESCRIPTION:
DSS Export Rating Curves= 0
DSS Export Rating Curve Sorted= 0
DSS Export Volume Flow Curves= 0
DXF OffsetX= 0
DXF OffsetY= 0
DXF ScaleX= 0
DXF ScaleY= 0

--- TOMSCR.p01 (plan) ---

Plan Title=Floodplain
Program Version=4.00
Geom File=g01
Flow File=f01
K Sum by GR=0
Std Step Tol=0.01
Critical Tol=0.01
Num of Std Step Trials=20
Max Error Tol=0.3
Flow Tol Ratio=0.001
Split Flow NTrial=30
Split Flow Tol=0.02
Split Flow Ratio=0.02
Log Output Level=0
Friction Slope Method=1
Unsteady Friction Slope Method=2
Unsteady Bridges Friction Slope Method=1
Global Log Level=0
CheckData=False
Run HTab=0
Run UNet=0
Run PostProcess=0
UNET Theta=0
UNET Theta Warmup=0
UNET ZTol=0
UNET ZSATol=0
UNET MxIter=0
UNET MaxInSteps=0
UNET DtIC=0
UNET DtMin=0
UNET MaxCRTS=0
UNET WFStab=0
UNET SFStab=0
UNET WFX=0
UNET SFX=0
UNET DSS MLevel=0
UNET DZMax Abort=0
UNET Convert EG Bridges=0
UNET Use Existing IB Tables=0
UNET Froude Limit=0
UNET Froude Power=0
Write IC File=0
Echo Input=False
Echo Output=False
Write Detailed=0

--- TOMSCR.f01 (steady flow) ---

Flow Title=NFF Regression Equation
Program Version=4.00
Number of Profiles= 1
Profile Names=P100yr
River Rch & RM=TOMSCR,Main            ,7872.1
     486
River Rch & RM=TOMSCR,Main            ,7179.6
     517
River Rch & RM=TOMSCR,Main            ,4782.8
     540
River Rch & RM=TOMSCR,Main            ,4484.5
     613
River Rch & RM=TOMSCR,Main            ,4188.9
     677
River Rch & RM=TOMSCR,Main            ,3283.9
     689
River Rch & RM=TOMSCR,Main            ,2375.7
     765
Boundary for River Rch & Prof#=TOMSCR,Main            , 1
Up Type= 0
Dn Type= 3
Dn Slope=0.0001
DSS Import GetInterval= 0
DSS Import GetPeak= 0
DSS Import FillOption= 0

--- TOMSCR.g01 (geometry) ---

Geom Title=USGS 10m DEM
Program Version=4.00

River Reach=TOMSCR          ,Main
Reach XY= 30
     1545443.443      447558.278     1545550.905      447557.792
     1545653.496      447494.011      1545823.63      447549.553
     1545925.554      447716.868     1546111.248      447596.578
     1546301.266      447587.886     1546440.202      447463.471
     1546585.176       447577.34     1546522.168      447680.175
      1546538.31      447723.144     1546687.356      447727.681
       1546854.7      447589.005     1547068.586        447524.2
     1547335.728      447583.223     1548322.511       447270.67
     1548714.644      447262.592     1549225.293       447406.26
     1549478.589      447402.883     1549587.738      447253.357
     1549856.607      447214.144     1550306.013      446853.709
     1550636.656      446699.122     1550824.723       446670.04
     1550889.364      446608.767     1551302.562      446493.555
     1551654.247       446633.29     1551848.594      446574.507
     1551981.089      446623.046     1552209.083      446562.884

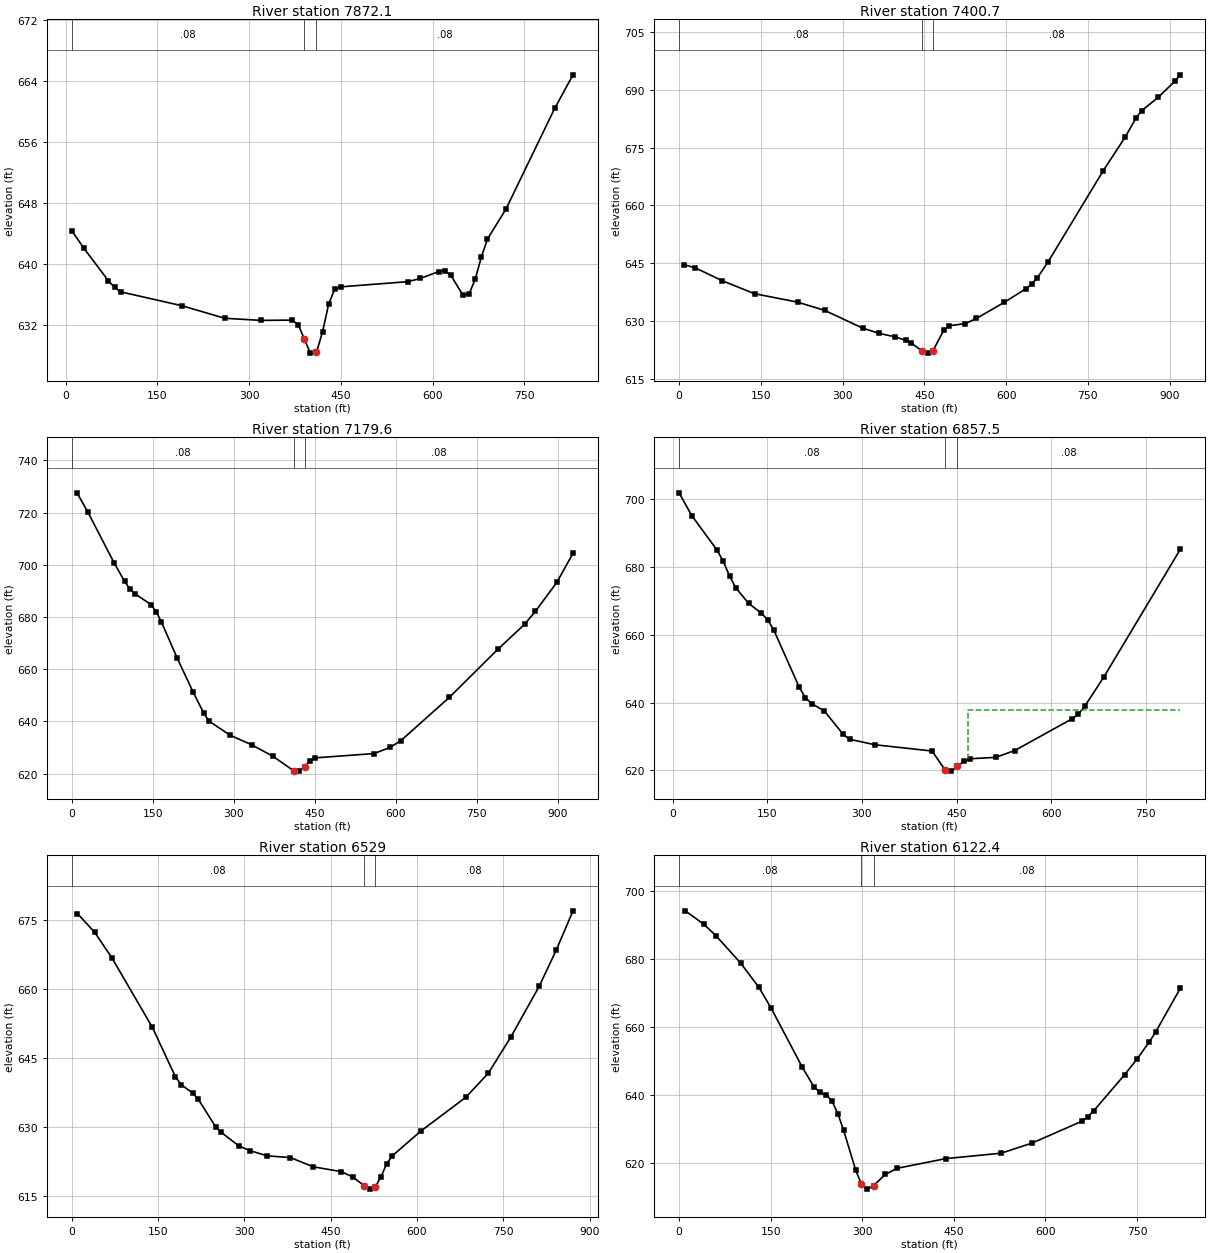
Type RM Length L Ch R = 1 ,7872.1  ,449.6,471.4,494.4
XS GIS Cut Line= 3
     1545485.945      447967.746     1545453.418      447558.979
     1545400.288      447143.031
#Sta/Elev= 30
      10  644.37      30  642.03      70  637.77      80   636.9      90  636.32
     190   634.5     260  632.85     320  632.57   370.1  632.61   380.1  632.03
   390.1  630.16  400.02  628.27   410.1  628.38     420  631.07     430  634.71
     440   636.7     450  636.98   559.8  637.66   579.8  638.08   609.7  638.98
   619.7  639.11   629.7  638.49   649.7  635.87   659.7  636.05   669.6  638.01
   679.6  640.89   689.6  643.26   719.6  647.16   799.4  660.41   829.4  664.83
#Mann= 3 , 0 , 0
      10     .08       0   390.1    .045       0   410.1     .08       0
Bank Sta=390.1,410.1
XS Rating Curve= 0 ,0
Exp/Cntr=0.3,0.1

Type RM Length L Ch R = 1 ,7400.7  ,252.1,221,189.4
XS GIS Cut Line= 4
     1545596.964       447979.95     1545720.986      447732.362
     1545897.464      447557.319     1545913.035      447163.321
#Sta/Elev= 30
     9.9   644.6    29.7   643.8    79.1  640.46   138.5  637.08   217.6  634.89
     267  632.76   336.6  628.16   366.4  626.81   396.2  625.88   416.1  624.96
   426.1  624.26   445.9  622.21   455.9  621.65   465.9  622.28   485.7  627.61
   495.7  628.76   525.5  629.32   545.7  630.66   596.3  634.81   636.7   638.4
   646.8  639.54   656.9  641.11   677.1  645.35   778.2  669.01   818.7  677.79
   838.9  682.82     849  684.63   879.3   688.1   909.7  692.27   919.8  693.93
#Mann= 3 , 0 , 0
       0     .08       0   445.9    .045       0   465.9     .08       0
Bank Sta=445.9,465.9
XS Rating Curve= 0 ,0
Exp/Cntr=0.3,0.1

Type RM Length L Ch R = 1 ,7179.6  ,319.6,322.1,323.9
XS GIS Cut Line= 4
     1546187.041      448043.166      1546058.94      447823.548
     1545940.083      447585.732     1546060.868       447195.84
#Sta/Elev= 30
     9.8  727.58    29.3  720.42    78.2  700.88    97.8   693.7   107.6  690.77
   117.3  688.87   146.7   684.8   156.5  682.05   166.2  678.05   195.6  664.15
   224.9  651.21   244.5  643.17   254.2  640.13   293.6   634.7     333  631.09
   372.4   626.7   411.6  621.03   421.6  620.98   431.6  622.74   441.3  624.94
   451.2  626.07   559.9  627.71   589.8  630.09   609.7  632.68   699.3  649.23
   788.9  667.61   838.7  677.22   858.6  682.17   898.4  693.29   928.3  704.43
#Mann= 3 , 0 , 0
       0     .08       0   411.6    .045       0   431.6     .08       0
Bank Sta=411.6,431.6
XS Rating Curve= 0 ,0
Exp/Cntr=0.3,0.1

Type RM Length L Ch R = 1 ,6857.5  ,301.7,328.5,347.8
XS GIS Cut Line= 3
     1546283.015      448026.023     1546313.183       447686.94
     1546134.834      447258.142
#Sta/Elev= 30
      10  701.83      30  695.14    70.1  684.98    80.1  681.61    90.1  677.28
   100.1  673.78   120.1  669.26   140.2  666.37   150.2  664.45   160.2  661.38
   200.2  644.63   210.3  641.38   220.3  639.66   240.3  637.52   270.3  630.58
   280.3  629.17   320.4  627.55   411.1   625.7   431.4  620.24   441.4  619.77
   451.4  621.14   461.6  622.71   471.7  623.42   512.1  623.83   542.3  625.85
   633.2   635.2   643.3  636.59   653.4  638.95   683.7  647.58   804.8  685.19
#Mann= 3 , 0 , 0
      10     .08       0   431.4    .045       0   451.4     .08       0
#XS Ineff= 2 , 0
                          468.83          637.72
Permanent Ineff=
       F       F
Bank Sta=431.4,451.4
XS Rating Curve= 0 ,0
Exp/Cntr=0.3,0.1

Type RM Length L Ch R = 1 ,6529    ,421.5,406.6,391.4
XS GIS Cut Line= 4
     1546362.894      447996.749     1546419.296      447620.737
     1546572.051      447428.032     1546633.152      447190.675
#Sta/Elev= 30
      10   676.5      40  672.39      70  666.83   140.1  651.76   180.1  641.04
   190.1  639.29   210.1  637.48   220.1  636.08   250.1  630.12   260.1  628.89
   290.2     626   310.2  624.91   340.2   623.8   380.2  623.43   419.6  621.43
   468.7  620.37   488.4   619.2   507.9  617.35   517.9  616.57   527.9   617.1
   537.6  619.27   547.4   622.1   557.3  623.82   606.5  629.17   684.9  636.54
   724.2   641.8   763.4   649.7   812.4  660.66   841.8  668.47   871.2  677.09
#Mann= 3 , 0 , 0
       0     .08       0   507.9    .045       0   527.9     .08       0
Bank Sta=507.9,527.9
XS Rating Curve= 0 ,0
Exp/Cntr=0.3,0.1

Type RM Length L Ch R = 1 ,6122.4  ,373.1,360.7,348.4
XS GIS Cut Line= 4
        1546565.      448010.849     1546651.953      447818.143
     1546668.404      447644.238     1546677.804      447209.475
#Sta/Elev= 30
    10.1  694.26    40.3  690.34    60.4  686.95   100.7   678.9   130.9   671.7
     151  665.53   201.3  648.39   221.1  642.38   230.8   640.8   240.5  640.09
   250.2  638.39   259.9  634.59   269.6   629.6   289.1  618.02   298.5  613.85
   308.5  612.34   318.5  613.37   337.6  616.65     357  618.47   436.7  621.32
   527.7  622.92   578.2   625.9   659.2  632.28   669.3  633.61   679.4  635.46
   729.9  646.05   750.2  650.67   770.4  655.72   780.5  658.58     821  671.48
#Mann= 3 , 0 , 0
       0     .08       0   298.5    .045       0   318.5     .08       0
Bank Sta=298.5,318.5
XS Rating Curve= 0 ,0
Exp/Cntr=0.3,0.1

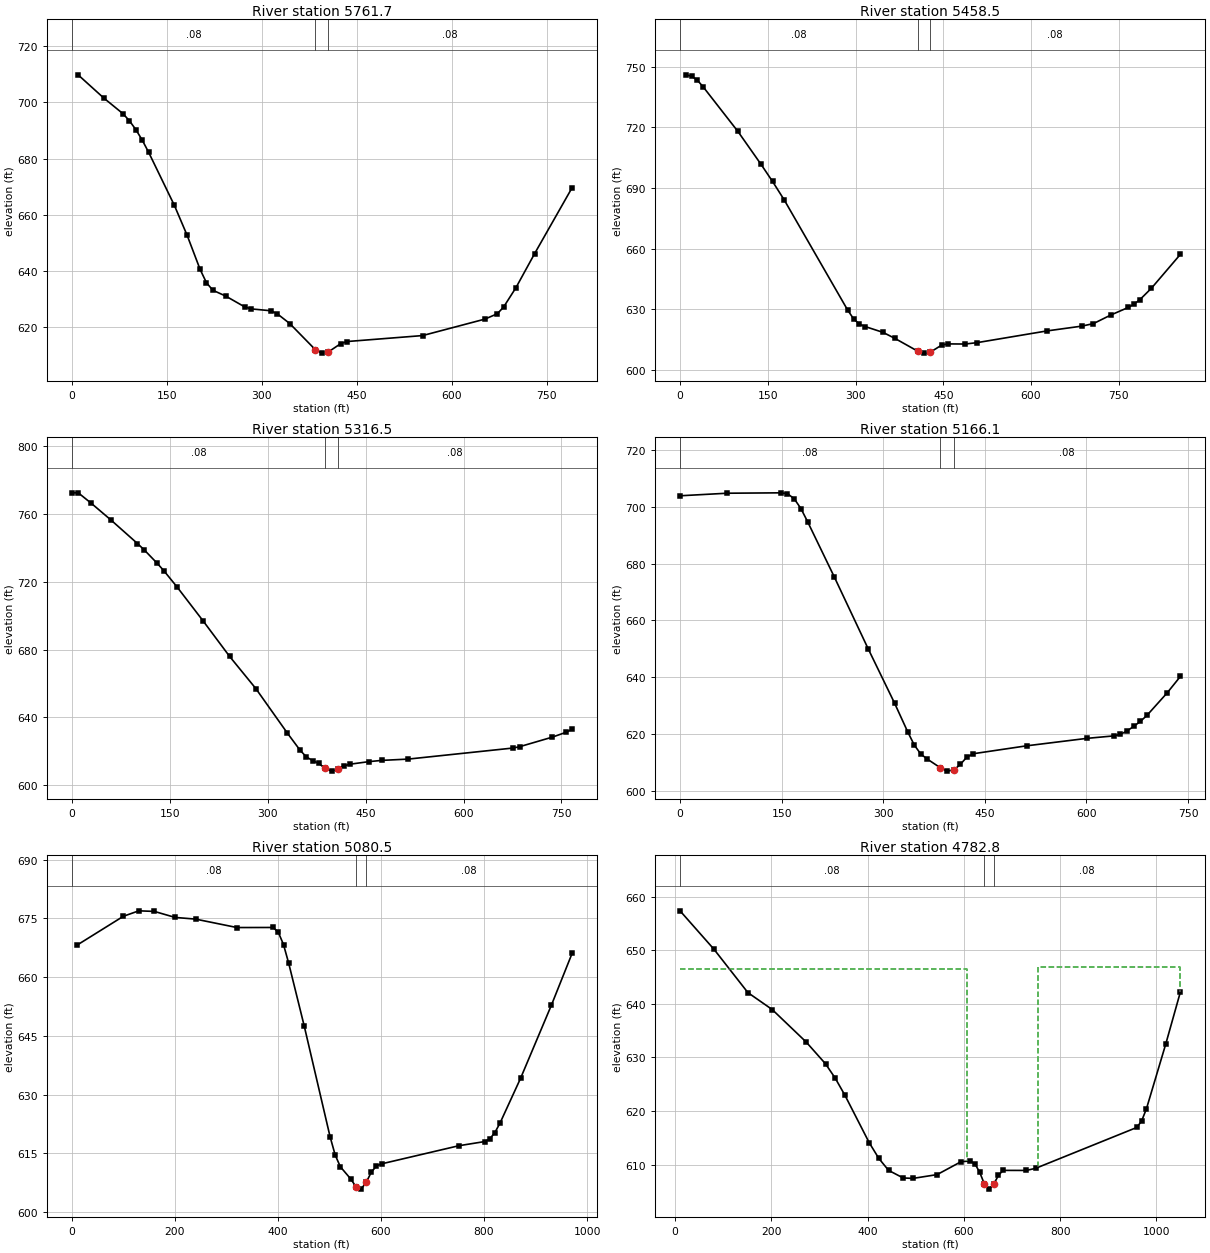
Type RM Length L Ch R = 1 ,5761.7  ,284.9,303.2,320.5
XS GIS Cut Line= 4
     1547056.532      447967.593     1546997.781      447659.146
     1546924.341      447493.907     1546898.637      447200.148
#Sta/Elev= 30
    10.1  709.78    50.6  701.54      81  695.95    91.2  693.43   101.3  690.29
   111.4  686.55   121.5  682.22   162.1  663.36   182.3  652.68   202.6  640.65
   212.7  635.88   222.8   633.2   243.1  631.13   273.5  627.23   283.6  626.57
     314  625.92     324  624.91   344.1  621.38   384.4  612.11   394.4  610.85
   404.4  611.17   424.5  614.21   434.5  614.97   553.8  617.09   652.1  622.94
   671.7  624.84   681.6  627.21   701.2  634.14   730.7  646.26   789.7  669.63
#Mann= 3 , 0 , 0
       0     .08       0   384.4    .045       0   404.4     .08       0
Bank Sta=384.4,404.4
XS Rating Curve= 0 ,0
Exp/Cntr=0.3,0.1

Type RM Length L Ch R = 1 ,5458.5  ,156.2,142,128.3
XS GIS Cut Line= 4
      1547141.46       447973.39      1547194.95      447681.646
     1547280.523      447424.139     1547303.484      447137.604
#Sta/Elev= 30
     9.9  746.03    19.8  745.36    29.7  743.34    39.5   740.1    98.9  718.05
   138.4  701.79   158.2  693.27     178  684.22   286.7  629.61   296.6  625.39
   306.7  622.71   316.7   621.5   346.9  618.66     367  615.72   407.2  609.21
   417.2  608.38   427.2  608.74   447.4  612.37   457.4  612.94   487.6  612.88
   507.7  613.56   627.4  619.37   686.9  621.74   706.7  622.98   736.5  627.24
   766.2  630.96   776.1  632.61     786  634.78   805.9  640.49   855.4  657.24
#Mann= 3 , 0 , 0
       0     .08       0   407.2    .045       0   427.2     .08       0
Bank Sta=407.2,427.2
XS Rating Curve= 0 ,0
Exp/Cntr=0.3,0.1

Type RM Length L Ch R = 1 ,5316.5  ,147,150.3,153.7
XS GIS Cut Line= 4
     1547289.121      447946.254     1547394.147      447684.609
     1547342.555      447498.509     1547346.241      447207.383
#Sta/Elev= 30
       0  772.51    10.1  772.51    30.2  766.27    60.4  756.38   100.7  742.59
   110.8  738.94   130.9  730.94     141   726.6   161.1  717.07   201.4  696.83
   241.7  676.01   281.9  657.01   330.2  630.73   349.5   620.7   359.2   616.7
   368.8  614.46   378.5  612.81   387.8  609.87  397.95  608.25   407.8  609.74
   417.1  611.36   426.8  612.37   455.7  613.88   475.1  614.59   515.2  615.35
   675.8  621.88   685.9  622.67   736.1  628.33   756.2  631.06   766.2   632.9
#Mann= 3 , 0 , 0
       0     .08       0   387.8    .045       0   407.8     .08       0
Bank Sta=387.8,407.8
XS Rating Curve= 0 ,0
Exp/Cntr=0.3,0.1

Type RM Length L Ch R = 1 ,5166.1  ,87,85.6,84
XS GIS Cut Line= 4
      1547596.83       447907.56       1547517.6      447631.174
     1547493.646      447457.973     1547462.323       447183.43
#Sta/Elev= 30
       0  703.87    69.4  704.77   148.7  704.91   158.6  704.61   168.5  702.84
   178.5  699.36   188.4  694.71     228  675.15   277.6  650.03   316.7  630.81
   336.1   620.7   345.8  616.05   355.5  612.84   365.2  611.06   384.4  608.01
   394.4  606.84   404.4  607.27   413.8  609.22   423.5  611.79   433.2  612.98
   511.7  615.76   600.5  618.38     640  619.25   649.9  619.77   659.7  620.96
   669.6  622.58   679.5  624.33   689.3  626.48     719  634.37   738.7  640.21
#Mann= 3 , 0 , 0
       0     .08       0   384.4    .045       0   404.4     .08       0
Bank Sta=384.4,404.4
XS Rating Curve= 0 ,0
Exp/Cntr=0.3,0.1

Type RM Length L Ch R = 1 ,5080.5  ,300.6,297.8,295.1
XS GIS Cut Line= 3
     1547694.438      448053.617     1547585.957      447502.785
     1547504.091      447101.552
#Sta/Elev= 30
      10  668.15   100.3  675.55   130.3  676.94   160.4  676.79   200.5  675.26
   240.6  674.82   320.8  672.67     391  672.69     401  671.44     411  668.33
   421.1  663.55   451.1  647.59   501.3   619.3   511.3  614.58   521.3  611.59
   541.4  608.49   551.4  606.53   561.4  605.88   571.4  607.58   581.4  610.21
   591.4   611.8   601.4  612.34   751.2  616.96   801.1  618.02   811.1  618.69
   821.1  620.32   831.1  622.74     871  634.18     931  652.91   970.9  666.05
#Mann= 3 , 0 , 0
       0     .08       0   551.4    .045       0   571.4     .08       0
Bank Sta=551.4,571.4
XS Rating Curve= 0 ,0
Exp/Cntr=0.3,0.1

Type RM Length L Ch R = 1 ,4782.8  ,300.7,298.3,295.9
XS GIS Cut Line= 4
     1548028.724       448074.73     1547897.417      447504.923
     1547839.022      447320.543     1547760.886       447060.09
#Sta/Elev= 30
    10.1  657.37    80.7  650.19   151.2   642.1   201.6  638.95   272.2  632.89
   312.5  628.81   332.7  626.13   352.9  622.93   403.3  614.09   423.4  611.14
   443.6  608.92   473.8  607.51     494  607.42   544.4  608.13   594.4  610.55
   613.8  610.66   623.4  610.09   633.1  608.54   642.4  606.44   652.4  605.42
   662.4  606.39   671.8  607.97   681.4  608.92   729.8  608.91   749.1   609.3
   959.4  616.93   969.5  618.14   979.6  620.44  1019.9  632.58  1050.1  642.23
#Mann= 3 , 0 , 0
    10.1     .08       0   642.4    .045       0   662.4     .08       0
#XS Ineff= 2 , 0
          606.09  646.59  753.81          646.81
Permanent Ineff=
       F       F
Bank Sta=642.4,662.4
XS Rating Curve= 0 ,0
Exp/Cntr=0.3,0.1

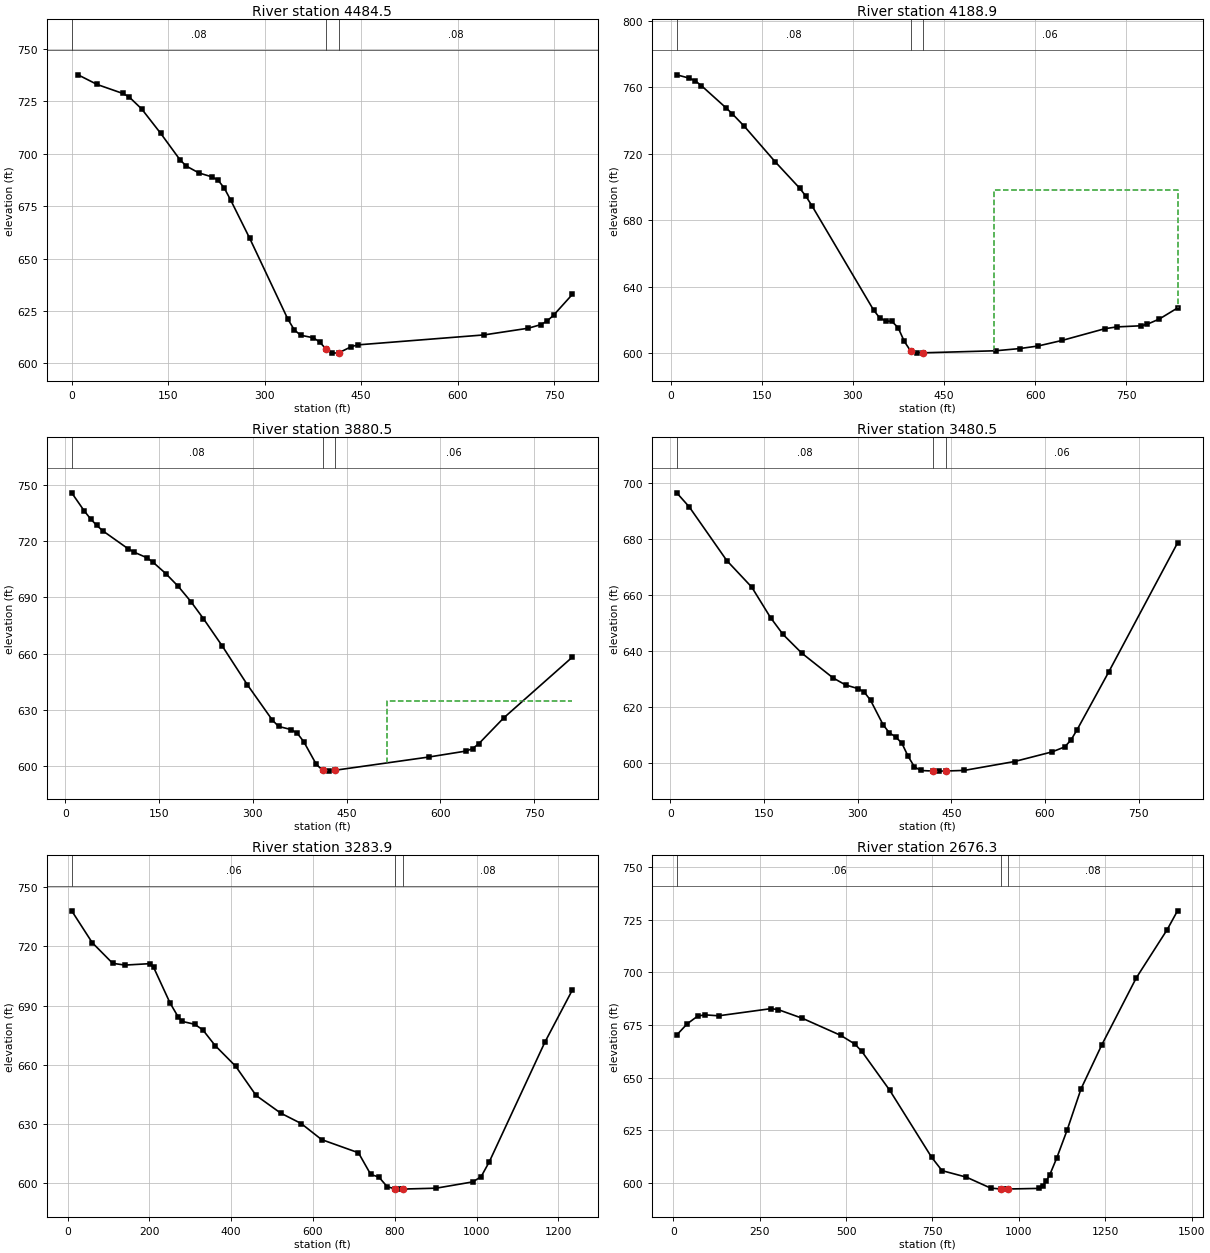
Type RM Length L Ch R = 1 ,4484.5  ,285.3,295.5,305.8
XS GIS Cut Line= 4
     1548282.975      447699.538     1548176.488      447391.091
     1548103.048      447218.508      1548014.92      446968.813
#Sta/Elev= 30
     9.9   737.6    39.6  732.99    79.1  728.76      89  727.15   108.8  721.33
   138.4  709.68   168.1   697.2     178  694.12   197.8  690.82   217.5     689
   227.4  687.44   237.3  683.57   247.2  677.88   276.9  659.58   336.2  621.05
   346.1  616.01   355.9  613.44   375.7  612.23   385.5  610.22   395.3  606.91
   405.3   604.9   415.3  605.06   434.9  607.99   444.8  608.83   641.4  613.59
     710  616.78   729.6  618.49   739.4  620.26   749.2  622.94   778.7  632.97
#Mann= 3 , 0 , 0
       0     .08       0   395.3    .045       0   415.3     .08       0
Bank Sta=395.3,415.3
XS Rating Curve= 0 ,0
Exp/Cntr=0.3,0.1

Type RM Length L Ch R = 1 ,4188.9  ,303.9,308.4,312.9
XS GIS Cut Line= 3
     1548429.855      447670.162     1548433.849      447245.083
     1548436.289      446835.818
#Sta/Elev= 30
    10.1  767.63    30.4  765.66    40.5  764.02    50.6  761.13    91.1  747.77
   101.2  744.26   121.5  736.55   172.1  715.24   212.5   699.3   222.7  694.48
   232.8  688.62     334  625.95   344.1  621.16   354.2  619.26   364.4  618.97
   374.5  615.25   384.6  607.02   394.9   601.3   404.9   599.9   414.9  600.08
   534.9  601.32   574.8  602.65   604.8  604.19   644.7  607.58   714.6  614.61
   734.5   615.7   774.5  616.39   784.5   617.3   804.4  620.44   834.4  627.11
#Mann= 3 , 0 , 0
    10.1     .08       0   394.9    .045       0   414.9     .06       0
#XS Ineff= 2 , 0
                          531.73          697.95
Permanent Ineff=
       F       F
Bank Sta=394.9,414.9
XS Rating Curve= 0 ,0
Exp/Cntr=0.3,0.1

Type RM Length L Ch R = 1 ,3880.5  ,400.8,400,399.2
XS GIS Cut Line= 3
     1548662.405      447673.976     1548740.488      447269.986
     1548815.413      446877.014
#Sta/Elev= 30
      10  745.61    30.1  735.97    40.1  731.77    50.2  728.21    60.2  725.26
   100.4  715.79   110.4  713.92   130.5  711.01   140.5  708.55   160.6  702.59
   180.6  695.76   200.7  687.71   220.8   678.6   250.9  664.05     291  643.45
   331.2  624.54   341.2  621.18   361.3  619.51   371.3  617.43   381.4  613.06
   401.4  601.04   411.5  597.86   421.5  597.38   431.5  597.85   581.5  604.89
   641.5  608.09   651.5  609.36   661.5  611.96   701.5  625.74   811.5  658.16
#Mann= 3 , 0 , 0
      10     .08       0   411.5    .045       0   431.5     .06       0
#XS Ineff= 2 , 0
                          513.91          634.68
Permanent Ineff=
       F       F
Bank Sta=411.5,431.5
XS Rating Curve= 0 ,0
Exp/Cntr=0.3,0.1

Type RM Length L Ch R = 1 ,3480.5  ,199.8,196.6,193.4
XS GIS Cut Line= 3
     1549061.436       447776.65     1549124.708      447380.999
     1549189.458      446974.431
#Sta/Elev= 30
      10  696.57    30.1  691.52    90.2  672.33   130.2  662.82   160.3  651.92
   180.3   645.9   210.4   639.2   260.4  630.35   280.5  627.82   300.5  626.51
   310.5  625.25   320.5  622.35   340.6  613.61   350.6  610.71   360.6  609.25
   370.6  607.03   380.6  602.35   390.7  598.56   400.7  597.21   420.8     597
   430.8  596.98   440.8  597.01     471  597.25   551.3  600.42   611.5  603.87
   631.6  605.64   641.7  608.11   651.7  611.87   701.9  632.35   812.4  678.61
#Mann= 3 , 0 , 0
      10     .08       0   420.8    .045       0   440.8     .06       0
Bank Sta=420.8,440.8
XS Rating Curve= 0 ,0
Exp/Cntr=0.3,0.1

Type RM Length L Ch R = 1 ,3283.9  ,621.2,607.6,594.1
XS GIS Cut Line= 4
     1549116.516       448165.88     1549311.131      447607.738
     1549325.819      447137.725     1549301.727      446966.151
#Sta/Elev= 30
      10  738.02    60.1  721.91   110.2  711.41   140.3  710.52   200.4  711.23
   210.4  709.34   250.5   691.3   270.5   684.2   280.5  681.97   310.6  680.52
   330.6   677.7   360.7  669.74   410.8  659.29   460.9  644.44     521   635.5
   571.1  630.22   621.1  622.07   711.2  615.39   741.2  604.42   761.2  603.06
   781.2  598.26   801.2  597.01   811.2  596.96   821.2     597   901.3  597.44
   991.3  600.65  1011.3  603.31  1031.3  610.86  1167.2  671.48  1234.6  698.01
#Mann= 3 , 0 , 0
      10     .06       0   801.2    .045       0   821.2     .08       0
Bank Sta=801.2,821.2
XS Rating Curve= 0 ,0
Exp/Cntr=0.3,0.1

Type RM Length L Ch R = 1 ,2676.3  ,303.7,300.6,297.5
XS GIS Cut Line= 4
     1550215.013      448171.273     1549979.777      447482.776
     1549750.277      447058.203     1549670.446      446822.445
#Sta/Elev= 30
    10.1  670.26    40.4  675.59    70.7  679.25    90.9  679.85   131.4   679.4
   282.9   682.8   303.2  682.36   373.9  678.19     485  670.05   525.5  665.95
   545.7  662.44   626.5  643.94   747.7  612.07   777.8  605.73   848.2  602.64
   918.6  597.42   948.8     597   958.8  596.94   968.8     597  1059.4  597.29
  1069.4  598.55  1079.5  600.85  1089.5  603.77  1109.7  611.76  1139.8  625.06
    1180  644.67  1240.1  665.59  1339.6  697.37  1429.2  720.38  1459.1  729.33
#Mann= 3 , 0 , 0
    10.1     .06       0   948.8    .045       0   968.8     .08       0
Bank Sta=948.8,968.8
XS Rating Curve= 0 ,0
Exp/Cntr=0.3,0.1

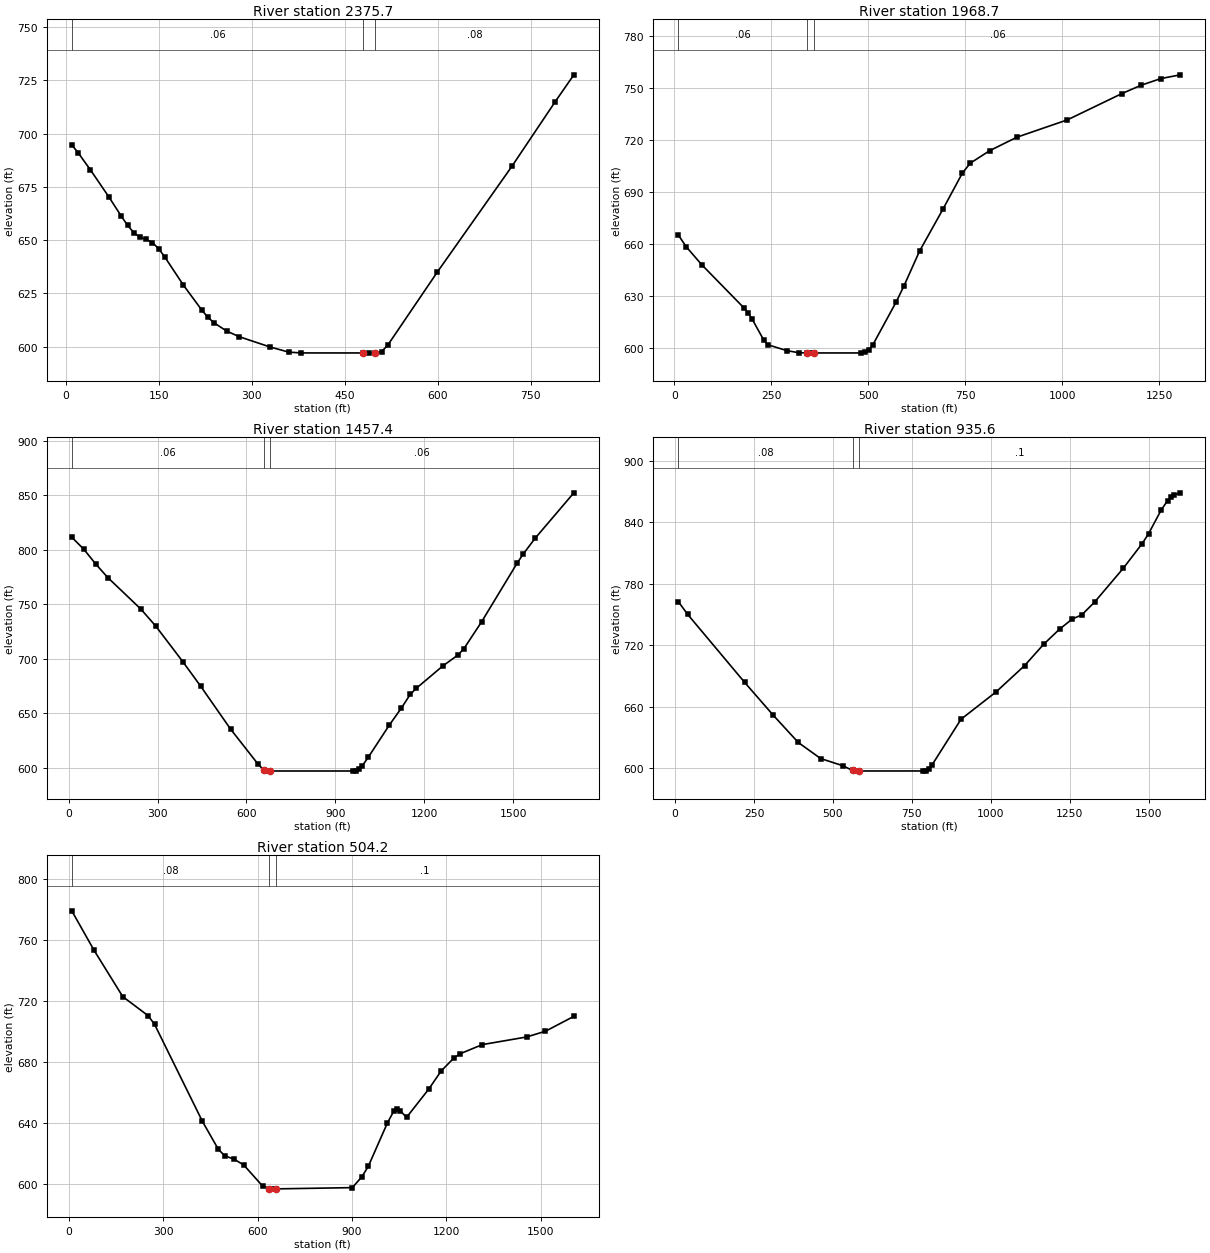
Type RM Length L Ch R = 1 ,2375.7  ,404.4,406.9,409.5
XS GIS Cut Line= 3
     1550370.262      447442.585     1550126.348      447113.669
     1549888.015      446780.583
#Sta/Elev= 30
      10  694.69      20  691.08    39.9  683.01    69.9   670.2    89.9  661.16
    99.9  656.95   109.9  653.48   119.8  651.27   129.8  650.32   139.8  648.82
   149.8  646.03   159.8  642.09   189.8  628.89   219.7  617.06   229.7  613.65
   239.7  611.05   259.7  607.27   279.6  604.66   329.6   599.8   359.5  597.41
   379.5  597.01   479.4     597   489.4  596.92   499.4  597.02   509.4  597.65
   519.4  600.74   599.3  635.06   719.2  684.58   789.1  714.96   819.1  727.56
#Mann= 3 , 0 , 0
      10     .06       0   479.4    .045       0   499.4     .08       0
Bank Sta=479.4,499.4
XS Rating Curve= 0 ,0
Exp/Cntr=0.3,0.1

Type RM Length L Ch R = 1 ,1968.7  ,495.6,511.4,521.8
XS GIS Cut Line= 3
     1550639.586      447241.802     1550329.763      446691.005
     1549756.015      446341.018
#Sta/Elev= 30
      10  665.11    30.1  658.37    70.2  647.96   180.6  622.69   190.6  619.95
   200.6  616.47   230.7  604.29   240.7  601.73   290.9  598.29     321  597.13
   341.1  597.01   351.1   596.9   361.1     597   481.5     597   491.5  597.31
   501.6  598.71   511.6  601.72   571.8  626.44   591.8  635.68     632  655.75
   692.1  679.85   742.3   700.7   762.4  706.39   812.5  713.61   882.7  721.39
  1013.1  731.42  1153.6  746.58  1203.7  751.42  1253.9  755.21    1304  757.37
#Mann= 3 , 0 , 0
      10     .06       0   341.1    .045       0   361.1     .06       0
Bank Sta=341.1,361.1
XS Rating Curve= 0 ,0
Exp/Cntr=0.3,0.1

Type RM Length L Ch R = 1 ,1457.4  ,522.1,521.8,526.8
XS GIS Cut Line= 4
     1551150.222      447345.077      1550903.51      446903.291
     1550805.973      446335.281     1550484.674      445801.696
#Sta/Elev= 30
    10.1  811.51    50.6  800.51    91.1  786.88   131.6  774.51   242.9  745.68
   293.5     730   384.6  697.46   445.3  674.79   546.4  635.38   637.4  603.85
   657.8  597.93   667.8  596.88   677.8     597     961     597   971.1  597.23
   981.2  598.69   991.3  601.85  1011.6  609.79  1082.3  639.15  1122.5  654.57
  1152.7  667.23  1172.7  672.75  1263.2  693.47  1313.4   703.3  1333.5  709.01
  1393.8   733.9  1514.3  787.96  1534.4  796.13  1574.6  810.57  1705.2  852.23
#Mann= 3 , 0 , 0
    10.1     .06       0   657.8    .045       0   677.8     .06       0
Bank Sta=657.8,677.8
XS Rating Curve= 0 ,0
Exp/Cntr=0.3,0.1

Type RM Length L Ch R = 1 ,935.6   ,421.5,431.3,436.5
XS GIS Cut Line= 4
     1551161.697      447230.327     1551310.871      446891.816
     1551356.771      446358.231      1550949.41      445795.958
#Sta/Elev= 30
      10  762.62      40  749.99     220  683.69   309.9  651.82   390.1  624.85
   460.9  609.17   531.6   602.1     562  597.49     572  596.86     582     597
   784.2  597.01   794.3  597.27   804.4  599.05   814.5  603.32   905.5  647.59
  1016.2  674.22  1106.7  699.98  1167.1  720.84  1217.4  735.59  1257.7  745.51
  1287.9  749.59  1328.1  761.96  1418.7  794.94  1479.1  819.25  1499.2  828.85
  1539.4  852.13  1559.6  861.24  1569.6   864.6  1579.7  866.77  1599.8  868.84
#Mann= 3 , 0 , 0
      10     .08       0     562    .045       0     582      .1       0
Bank Sta=562,582
XS Rating Curve= 0 ,0
Exp/Cntr=0.3,0.1

Type RM Length L Ch R = 1 ,504.2   ,522.6,504.2,490.3
XS GIS Cut Line= 4
      1551430.35      447378.864     1551677.062      446914.128
     1551768.605      446374.757     1551395.925      445996.132
#Sta/Elev= 30
    10.1  778.95    80.9  753.11     172  722.81     253  710.26   273.2  704.59
     425  641.16   475.6  622.88   495.8  618.67   526.2  616.38   556.6  612.56
   617.3  598.58   637.7  597.04   647.7  596.84   657.7     597     901  597.82
   931.4  604.95   951.7  611.73  1012.5  640.18  1032.7  647.89  1042.9  648.95
    1053  648.12  1073.2  643.79  1143.4  662.19  1183.5  674.25  1223.6  682.65
  1243.7  685.45  1313.8  691.41  1454.2  696.39  1514.3  700.16  1604.5  709.89
#Mann= 3 , 0 , 0
    10.1     .08       0   637.7    .045       0   657.7      .1       0
Bank Sta=637.7,657.7
XS Rating Curve= 0 ,0
Exp/Cntr=0.3,0.1
Stream Node=TOMSCR          ,Main            , 0 , 0 ,Upstream end
Stream Node=TOMSCR          ,Main            , 0 , 1 ,Downstream end

Chan Stop Cuts=-1
Use User Specified Reach Order=0